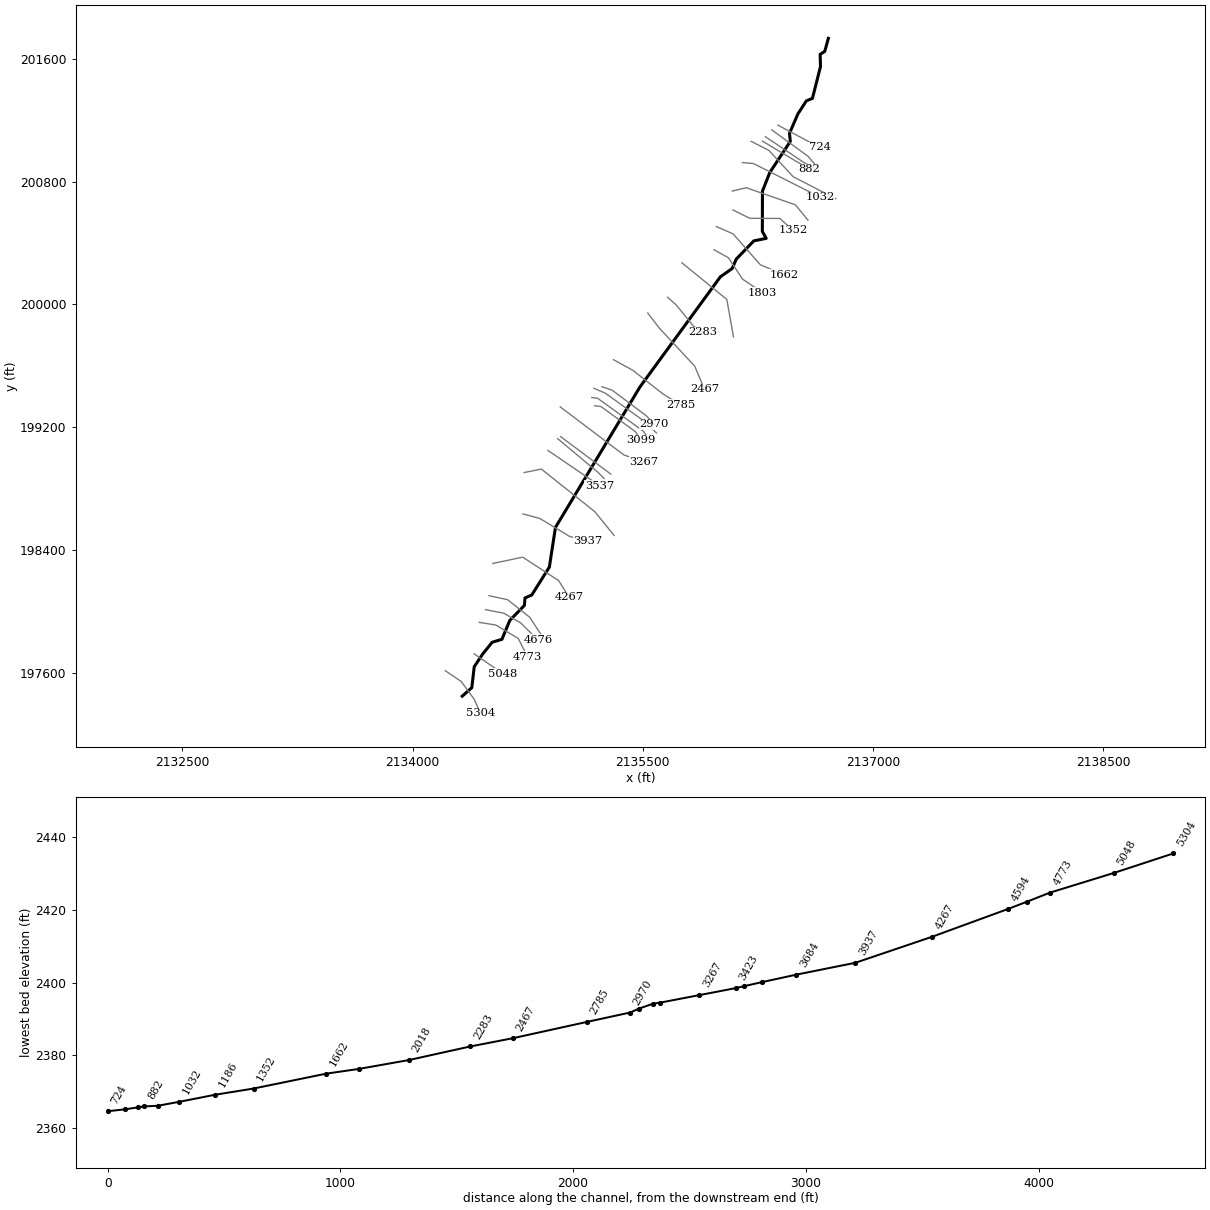
--- BACKCKT1.prj (project) ---

Proj Title=BACKCKT1
Current Plan=p01
Default Exp/Contr=0,0
English Units
Geom File=g01
Flow File=f01
Plan File=p01
Background Map Layer=Inundation Boundary (01pct Value_0)
BEGIN DESCRIPTION:
Stream Name: Back Creek Tributary 1
Flood Zone: Approximate
Monroe County, West Virginia
HEC-RAS Version: 5.0.7
Vertical Datum: NAVD88
Projection: NAD 1983 StatePlane West Virginia S FIPS 4702 (US Feet)
LiDAR: 2016, 1-meter
Land Use: 2016 NLCD
Hydrologic Method:
SIR2010-5033 regression equations
Model Notes:
KWSELs at sta 46, coincident peak with Back Creek
END DESCRIPTION:
DSS Export Rating Curves= 0
DSS Export Rating Curve Sorted= 0
DSS Export Volume Flow Curves= 0
DXF OffsetX= 0
DXF OffsetY= 0
DXF ScaleX= 0
DXF ScaleY= 0

--- BACKCKT1.p01 (plan) ---

Plan Title=Floodplain
Program Version=5.07
Short Identifier=Floodplain
Geom File=g01
Flow File=f01
Subcritical Flow
K Sum by GR= 0
Std Step Tol= 0.01
Critical Tol= 0.01
Num of Std Step Trials= 20
Max Error Tol= 0.3
Flow Tol Ratio= 0.001
Split Flow NTrial= 30
Split Flow Tol= 0.02
Split Flow Ratio= 0.02
Log Output Level= 0
Friction Slope Method= 1
Unsteady Friction Slope Method= 2
Unsteady Bridges Friction Slope Method= 1
Parabolic Critical Depth
Global Vel Dist= 0 , 0 , 0
Global Log Level= 0
CheckData=True
Encroach Param=-1 ,0,0, 0
Mapping Interval=1HOUR
Computation Time Step Use Courant=        0
Computation Time Step Use Time Series=    0
Computation Time Step Count To Double=0
Computation Time Step Max Doubling=0
Computation Time Step Max Halving=0
Computation Time Step Residence Courant=0
Run HTab= 0
Run UNet= 0
Run Sediment= 0
Run PostProcess= 0
Run WQNet= 0
Run RASMapper=-1
UNET Theta= 0
UNET Theta Warmup= 0
UNET ZTol= 0
UNET ZSATol= 0
UNET MxIter= 0
UNET Max Iter WO Improvement= 0
UNET MaxInSteps= 0
UNET DtIC= 0
UNET DtMin= 0
UNET MaxCRTS= 0
UNET WFStab= 0
UNET SFStab= 0
UNET WFX= 1
UNET SFX= 1
UNET 1D Methodology=Finite Difference
UNET DSS MLevel= 1
UNET Pardiso=0
UNET DZMax Abort= 0
UNET Use Existing IB Tables= 0
UNET Froude Reduction=False
UNET Froude Limit= 0
UNET Froude Power= 0
UNET D1 Cores= 0
UNET D2 Coriolis=0
UNET D2 Cores= 0
UNET D2 Theta= 1
UNET D2 Theta Warmup= 1
UNET D2 Z Tol= 0.01
UNET D2 Volume Tol= 0.01
UNET D2 Max Iterations= 20
UNET D2 Equation= 0
UNET D2 RampUpFraction=0.1
UNET D2 TimeSlices= 1
UNET D2 BCVolumeCheck=0
UNET D1D2 MaxIter= 0
UNET D1D2 ZTol=0.01
UNET D1D2 QTol=0.1
UNET D1D2 MinQTol=1
Write IC File= 0
Write IC File at Fixed DateTime=0
Write IC File at Sim End=0
Echo Input=False
Echo Parameters=False
Echo Output=False
Write Detailed= 0
HDF Write Warmup=0
HDF Write Time Slices=0
HDF Flush=0
HDF Face Node Velocities=0
HDF Compression= 1
HDF Chunk Size= 1
HDF Spatial Parts= 1
HDF Use Max Rows=0
HDF Fixed Rows= 1
Calibration Method= 0
Calibration Iterations= 20
Calibration Max Change=0.05
Calibration Tolerance=0.2
Calibration Maximum=1.5
Calibration Minimum=0.5
Calibration Optimization Method= 1
WQ AD Non Conservative
WQ ULTIMATE=-1
WQ Max Comp Step=1HOUR
WQ Output Interval=15MIN
WQ Output Selected Increments= 0
WQ Output face flow=0
WQ Output face velocity=0
WQ Output face area=0
WQ Output face dispersion=0
WQ Output cell volume=0
WQ Output cell surface area=0
WQ Output cell continuity=0
WQ Output cumulative cell continuity=0
WQ Output face conc=0
WQ Output face dconc_dx=0
WQ Output face courant=0
WQ Output face peclet=0
WQ Output face adv mass=0
WQ Output face disp mass=0
WQ Output cell mass=0
WQ Output cell source sink temp=0
WQ Output nsm pathways=0
WQ Output nsm derived pathways=0
WQ Output MaxMinRange=-1
WQ Daily Max Min Mean=-1
WQ Daily Range=0
WQ Daily Time=0
WQ Create Restart=0
WQ Fixed Restart=0
WQ System Summary=0
WQ Write To DSS=0
WQ Use Fixed Temperature=0
Sorting and Armoring Iterations= 10
XS Update Threshold= 0.02
Bed Roughness Predictor= 0
Hydraulics Update Threshold= 0.02
Energy Slope Method= 1
Volume Change Method= 1
Sediment Retention Method= 0
XS Weighting Method= 0
Number of US Weighted Cross Sections= 1
Number of DS Weighted Cross Sections= 1
Upstream XS Weight=0
Main XS Weight=1
Downstream XS Weight=0
Number of DS XS's Weighted with US Boundary= 1
Upstream Boundary Weight= 1
Weight of XSs Associated with US Boundary= 0
Number of US XS's Weighted with DS Boundary= 1
Downstream Boundary Weight= 0.5
Weight of XSs Associated with DS Boundary= 0.5
Percentile Method= 0
Sediment Output Level= 3
Mass or Volume Output= 0
Output Increment Type= 1
Profile and TS Output Increment= 1
XS Output Flag= 0
XS Output Increment= 10
Write Gradation File= 0
Read Gradation Hotstart= 0
Write HDF5 File= 1
Write Binary Output= 1
Write DSS Sediment File= 0
SV Curve= 0
Specific Gage Flag= 0

--- BACKCKT1.f01 (steady flow) ---

Flow Title=Flow
Program Version=5.07
Number of Profiles= 6
Profile Names=01pct,10pct,04pct,02pct,0_2pct,01plus
River Rch & RM=BACKCKT1,Main            ,5304
     541     285     379     457     756     799
River Rch & RM=BACKCKT1,Main            ,3937
     594     314     418     503     829     879
River Rch & RM=BACKCKT1,Main            ,1662
     632     336     445     536     882     935
River Rch & RM=BACKCKT1,Main            ,46
    1140     618     811     970    1570    1680
Boundary for River Rch & Prof#=BACKCKT1,Main            , 1
Up Type= 0
Dn Type= 1
Dn Known WS=2361.838
Boundary for River Rch & Prof#=BACKCKT1,Main            , 2
Up Type= 0
Dn Type= 1
Dn Known WS=2361.252
Boundary for River Rch & Prof#=BACKCKT1,Main            , 3
Up Type= 0
Dn Type= 1
Dn Known WS=2361.498
Boundary for River Rch & Prof#=BACKCKT1,Main            , 4
Up Type= 0
Dn Type= 1
Dn Known WS=2361.67
Boundary for River Rch & Prof#=BACKCKT1,Main            , 5
Up Type= 0
Dn Type= 1
Dn Known WS=2362.209
Boundary for River Rch & Prof#=BACKCKT1,Main            , 6
Up Type= 0
Dn Type= 1
Dn Known WS=2362.295
DSS Import GetInterval= 0
DSS Import GetPeak= 0
DSS Import FillOption= 0

--- BACKCKT1.g01 (geometry) ---

Geom Title=Geometry
Program Version=5.07

River Reach=BACKCKT1        ,Main
Reach XY= 30
2134324.04400001197446.0789999962134386.54399998197501.634000018
2134402.26488434 197637.934122862134456.65414946197719.823816851
2134519.35699999197797.6410000322134582.85299158197816.652020112
2134634.21457131197940.0374289452134729.25901157198037.556976914
2134732.89800002198085.835999995  2134777.237233198105.518227234
2134891.75200002198287.2240000222134931.68300001198545.905000001
2135482.46493094 199461.703734012136006.56136581200179.355537817
2136083.63190188200233.1681846082136109.63500004      200294.169
2136224.21800001200413.0919999932136305.10685481200429.578952268
2136279.77300002200474.7240000072136280.64100003200737.745000005
     2136328.384200858.405000016 2136462.0197631 201061.60036993
2136456.73835829201114.0862369392136511.54400003201240.349000037
2136566.61459962201325.5728070442136606.32285477201341.866041496
2136658.78240663201549.131275937 2136656.5290914201628.855991915
2136686.53001562201648.0629744982136709.96697666201733.133014306

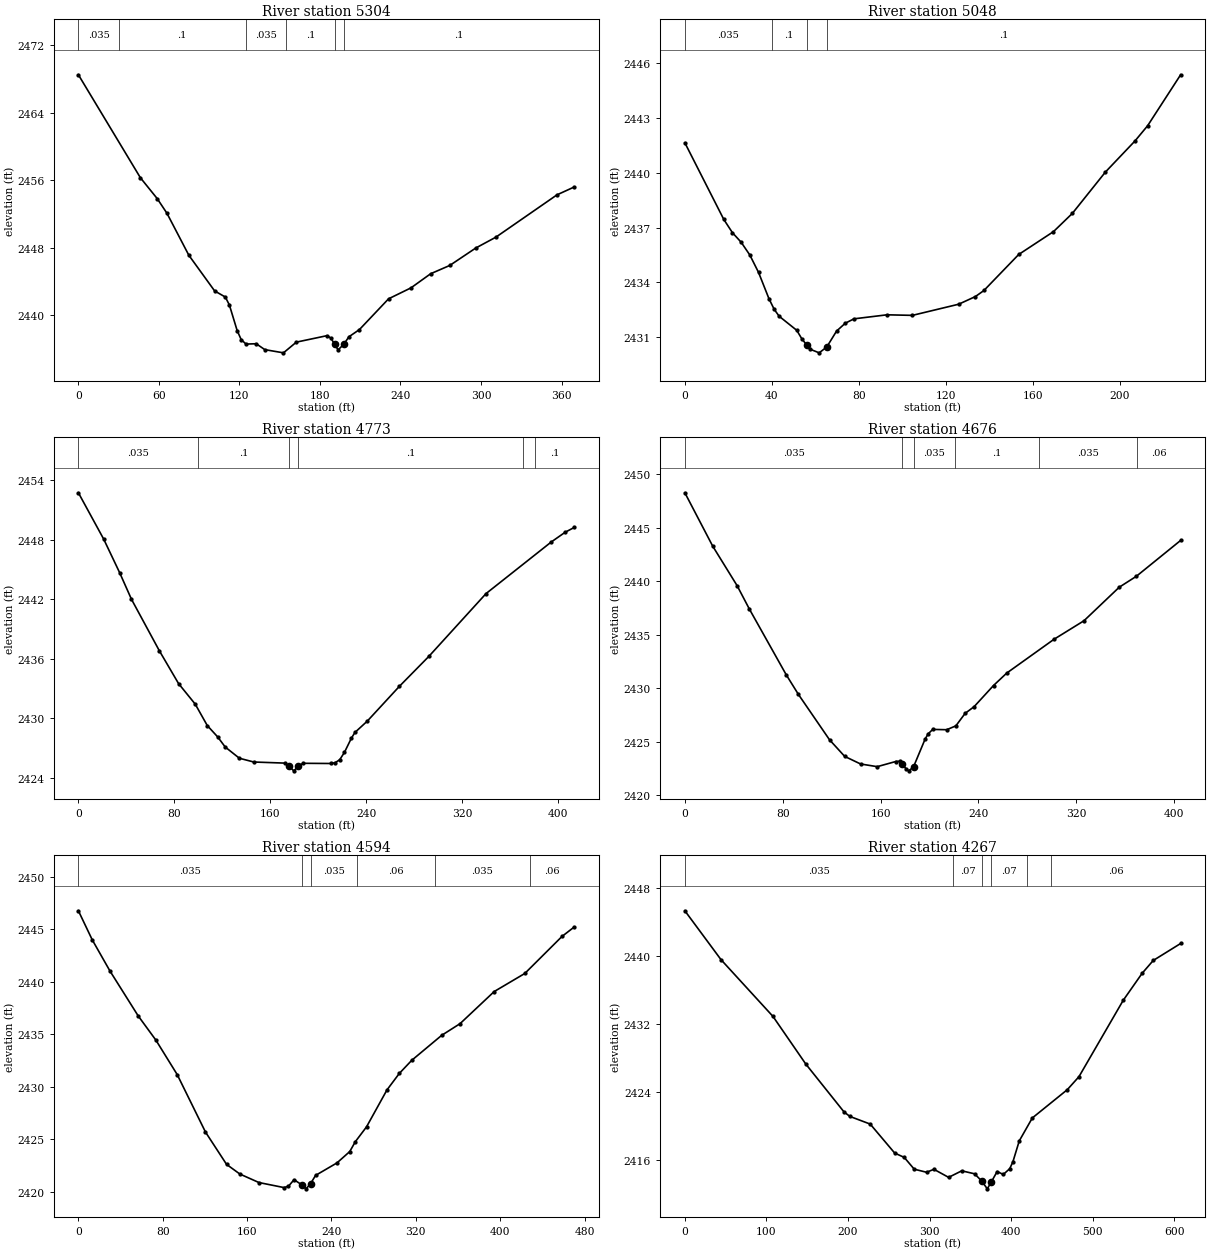
Type RM Length L Ch R = 1 ,5304    ,245.2,255.5,245.2
XS GIS Cut Line= 4
2134213.57552744197611.8515475732134317.06532111197542.219525907
2134402.02916406197425.9532145022134442.91402082197333.962286797
#Sta/Elev= 30
       0 2468.51    46.2 2456.29    58.7 2453.82      66 2452.07    82.3 2447.09
   101.5 2442.86   109.5 2442.13   112.5 2441.19   118.3 2438.15   121.3 2437.08
   124.9 2436.55   132.5 2436.59   138.9 2435.89   152.8 2435.51   162.4 2436.78
   185.3 2437.55   188.2 2437.25     191  2436.5   193.5 2435.86   197.6  2436.5
   201.6 2437.42   209.4 2438.27   231.1 2441.92   247.8 2443.22   262.5  2444.9
   276.7 2445.88   296.1 2447.95   311.1 2449.24   356.6 2454.26   369.4 2455.19
#Mann= 6 ,-1 , 0
       0    .035       0      30      .1       0  124.73    .035       0
  154.73      .1       0     191    .045       0   197.6      .1       0
Bank Sta=191,197.6
XS Rating Curve= 0 ,0
Exp/Cntr(USF)=0,0
Exp/Cntr=0.3,0.1

Type RM Length L Ch R = 1 ,5048    ,269.5,275.6,275.1
XS GIS Cut Line= 2
2134401.19404974197722.7158415212134588.71507467197592.893593499
#Sta/Elev= 30
       0 2441.64    17.9 2437.45    21.9 2436.72    25.9  2436.2    29.9  2435.5
    33.9 2434.55    38.7 2433.11    41.1 2432.53    43.4 2432.15    51.5 2431.38
    53.8 2430.92    56.12430.575    57.6 2430.35    61.8 2430.15    65.32430.472
    69.8 2431.34    73.8 2431.77    77.8 2432.01      93 2432.23   104.7  2432.2
     126 2432.81   133.7 2433.23   137.6 2433.56   153.6 2435.53   169.6 2436.78
   178.3 2437.78   193.5 2440.04   207.1 2441.74   212.9 2442.57   228.1 2445.36
#Mann= 4 ,-1 , 0
       0    .035       0      40      .1       0    56.1    .045       0
    65.3      .1       0
Bank Sta=56.1,65.3
XS Rating Curve= 0 ,0
Exp/Cntr(USF)=0,0
Exp/Cntr=0.3,0.1

Type RM Length L Ch R = 1 ,4773    ,95.5,96.6,96.7
XS GIS Cut Line= 4
2134434.51383256 197927.213315372134543.82403986197909.468151846
2134689.73174891197821.6753110452134749.33255598197703.228137498
#Sta/Elev= 30
       0 2452.75    21.1 2448.08    34.4  2444.7    44.3 2442.01    67.6 2436.81
    83.6 2433.51    97.5 2431.44   107.5 2429.29   116.2 2428.14   122.5 2427.12
   134.3 2425.99   146.3 2425.61   172.1  2425.5   175.9 2425.18   179.7 2424.72
   183.6  2425.2   187.4 2425.48   210.8 2425.46   214.2 2425.54     218 2425.84
   221.9 2426.57   227.7    2428   230.7 2428.59     241 2429.73   267.8 2433.24
   292.4 2436.26   340.1 2442.59   394.5 2447.79   406.2 2448.78   413.6 2449.25
#Mann= 6 ,-1 , 0
       0    .035       0     100      .1       0   175.9    .045       0
   183.6      .1       0  371.03     .06       0  381.03      .1       0
Bank Sta=175.9,183.6
XS Rating Curve= 0 ,0
Exp/Cntr(USF)=0,0
Exp/Cntr=0.3,0.1

Type RM Length L Ch R = 1 ,4676    ,82.8,81.9,79.7
XS GIS Cut Line= 4
2134475.59510417198009.6913371492134594.40903291197986.915504163
2134706.01061455197922.7635745852134816.47340453197813.059979034
#Sta/Elev= 30
       0 2448.26    22.8 2443.27    42.7 2439.59    52.8 2437.39    82.9 2431.26
    92.9 2429.42   118.3 2425.19   130.7 2423.64   143.7 2422.93   157.3 2422.68
   172.4 2423.16   176.2 2423.19   177.92422.945   181.2 2422.42   183.2 2422.29
     187 2422.67   196.4 2425.24   198.9 2425.74   202.7 2426.16   214.1 2426.13
   221.6 2426.49   229.2 2427.66   236.5 2428.28   252.4 2430.26   263.2 2431.42
   301.9 2434.58   326.4 2436.31   355.2 2439.44   369.2 2440.46   405.4 2443.81
#Mann= 6 ,-1 , 0
       0    .035       0   177.9    .045       0     187    .035       0
  220.98      .1       0   289.7    .035       0   369.7     .06       0
Bank Sta=177.9,187
XS Rating Curve= 0 ,0
Exp/Cntr(USF)=0,0
Exp/Cntr=0.3,0.1

Type RM Length L Ch R = 1 ,4594    ,320.1,327.5,324.3
XS GIS Cut Line= 4
2134498.27987243198100.9848102422134619.65679093198074.721968228
2134763.74751874197960.4431151372134852.47333635197824.870065819
#Sta/Elev= 30
       0 2446.75    13.1 2443.99    29.9 2441.02    56.7 2436.74    73.5 2434.43
    93.7 2431.15   120.5 2425.68   140.5  2422.6   153.1 2421.68   171.2 2420.87
     195 2420.39   199.2 2420.52   204.5 2421.14   211.7 2420.66   215.9 2420.27
   220.2 2420.77   224.9 2421.55   245.2 2422.74   257.3 2423.82   262.6 2424.76
   273.2 2426.17   292.6 2429.69   304.3 2431.26   316.1 2432.51   344.5 2434.89
   361.9    2436   394.3 2439.06   423.3 2440.78   458.6 2444.31   470.1  2445.2
#Mann= 6 ,-1 , 0
       0    .035       0   211.7    .045       0   220.2    .035       0
  264.19     .06       0  338.09    .035       0  428.09     .06       0
Bank Sta=211.7,220.2
XS Rating Curve= 0 ,0
Exp/Cntr(USF)=0,0
Exp/Cntr=0.3,0.1

Type RM Length L Ch R = 1 ,4267    ,321.1,330,317.2
XS GIS Cut Line= 4
2134523.50801415198310.9884241942134718.24231893198351.858586926
 2134952.6714964198199.0112115812135021.02586629198089.771984931
#Sta/Elev= 30
       0 2445.33    44.3 2439.58     108  2432.9   148.2  2427.3   195.1 2421.66
   202.3 2421.13   227.2 2420.23   257.2 2416.82   268.9 2416.31   281.2 2414.92
   296.3 2414.56   305.3 2414.91   323.3 2413.96   339.4 2414.73   355.1 2414.38
   363.9 2413.53   370.7 2412.61   375.7 2413.43   382.8 2414.65   390.3  2414.3
   398.2 2414.98   402.1 2415.79   409.9 2418.25   425.9 2420.95   468.7 2424.27
   483.1 2425.81   537.3 2434.79   560.5 2437.97   574.1 2439.48   607.7 2441.48
#Mann= 6 ,-1 , 0
       0    .035       0  328.98     .07       0   363.9    .045       0
   375.7     .07       0  418.98    .035       0  448.98     .06       0
Bank Sta=363.9,375.7
XS Rating Curve= 0 ,0
Exp/Cntr(USF)=0,0
Exp/Cntr=0.3,0.1

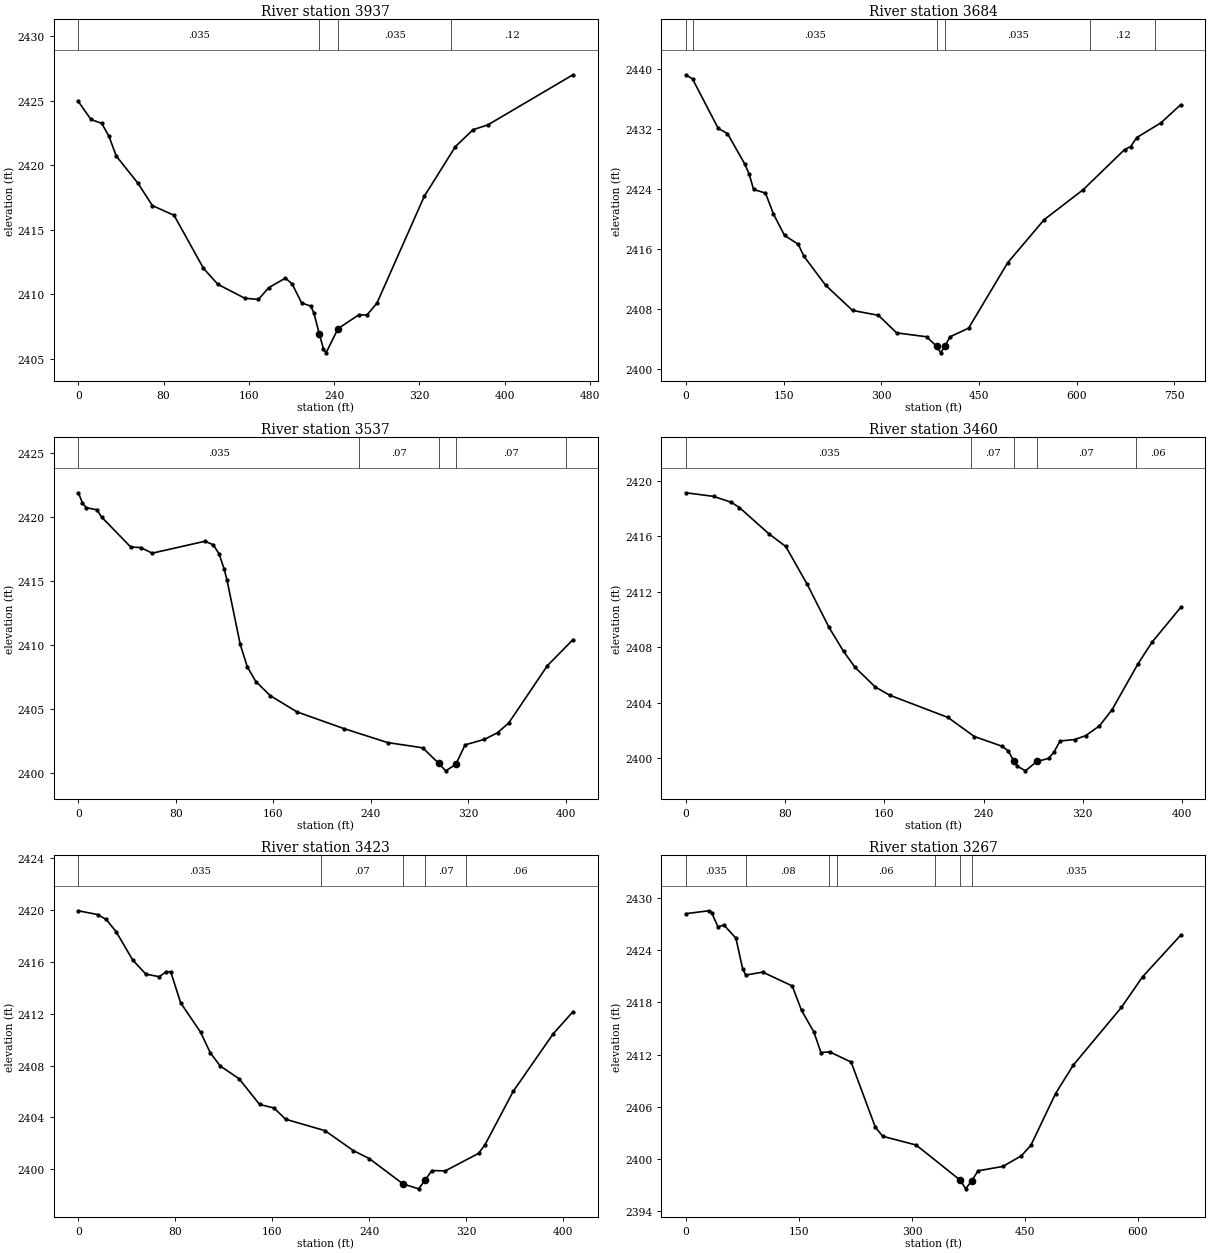
Type RM Length L Ch R = 1 ,3937    ,251.5,252.9,247.4
XS GIS Cut Line= 4
2134719.48211412198633.5720880592134829.30325856198604.632154223
 2135022.7322665198487.5175609542135142.62718482198454.444187146
#Sta/Elev= 30
       0 2424.94    11.8 2423.55      22 2423.24    28.8 2422.23    35.6 2420.71
    55.9 2418.61    69.5 2416.87    89.8 2416.12   117.4 2412.01   130.9 2410.77
   156.2 2409.69   168.9  2409.6   178.8 2410.52   194.3 2411.25   200.6  2410.8
   209.5 2409.33   218.1 2409.08     221 2408.55   226.12406.922     230 2405.76
   232.4 2405.46   243.72407.337   263.2 2408.41   270.8 2408.39   280.2 2409.32
   324.5 2417.58   353.8 2421.45   370.5 2422.76   384.1 2423.12   464.1 2427.01
#Mann= 4 ,-1 , 0
       0    .035       0   226.1    .045       0   243.7    .035       0
  349.69     .12       0
Bank Sta=226.1,243.7
XS Rating Curve= 0 ,0
Exp/Cntr(USF)=0,0
Exp/Cntr=0.3,0.1

Type RM Length L Ch R = 1 ,3684    ,145.4,147.4,147.1
XS GIS Cut Line= 4
2134727.65974885198903.3493260782134839.85235243198926.054972041
2135188.45079926 198648.244715562135313.99966517198493.312072523
#Sta/Elev= 30
       0 2439.26      10  2438.7    49.4 2432.12    63.6 2431.43    90.3 2427.35
      97 2426.02   103.7 2423.98     122  2423.5   134.3  2420.7   151.3 2417.85
   172.3 2416.68     181 2415.08   214.3 2411.22   255.7 2407.86   295.4 2407.21
   323.4 2404.87   369.5 2404.35   384.8 2403.08   391.1 2402.21   398.1 2403.17
   405.1 2404.33     434 2405.51   493.8  2414.2     550 2419.96   609.9 2423.95
   673.5  2429.3   682.8 2429.69   692.2  2430.9   729.3 2432.86   759.6 2435.27
#Mann= 6 ,-1 , 0
       0     .04       0      10    .035       0   384.8    .045       0
   398.1    .035       0  620.22     .12       0  720.22    .035       0
Bank Sta=384.8,398.1
XS Rating Curve= 0 ,0
Exp/Cntr(USF)=0,0
Exp/Cntr=0.3,0.1

Type RM Length L Ch R = 1 ,3537    ,76.8,76.1,74.4
XS GIS Cut Line= 2
2134882.39755252 199047.932958562135217.38732285 198818.82078403
#Sta/Elev= 30
       0 2421.89     3.3 2421.12     6.3 2420.73    15.2 2420.56    19.2 2419.98
      43 2417.65    51.2 2417.61    60.6 2417.17   103.8  2418.1   110.6 2417.83
   115.4 2417.13   119.6 2415.94     122 2415.05   132.8 2410.05   138.6 2408.29
   145.6 2407.14   157.4 2406.04   179.3 2404.77   217.9 2403.46   253.7 2402.37
   282.5 2401.96   295.6 2400.75   301.4 2400.16   309.72400.667   317.3 2402.19
   333.2 2402.62   343.9 2403.14   353.1  2403.9   384.8 2408.38   405.8 2410.41
#Mann= 5 ,-1 , 0
       0    .035       0     230     .07       0   295.6    .045       0
   309.7     .07       0     400     .06       0
Bank Sta=295.6,309.7
XS Rating Curve= 0 ,0
Exp/Cntr(USF)=0,0
Exp/Cntr=0.5,0.3

Type RM Length L Ch R = 1 ,3460    ,37,37.8,38.4
XS GIS Cut Line= 3
2134946.01752162 199124.13944233 2135209.0990183198904.759053098
2135248.49758275198864.522221318
#Sta/Elev= 30
       0 2419.16    22.2  2418.9    36.3 2418.48    43.1 2418.09      67 2416.18
    80.4 2415.28    97.8 2412.53   115.3 2409.43     127  2407.7   136.3 2406.54
   152.6 2405.12   164.2 2404.53   211.2 2402.92   232.5 2401.54   255.1 2400.83
   259.8  2400.5   264.4 2399.76   266.8 2399.42   273.7 2399.06   282.92399.736
   292.4 2399.96   296.6  2400.4   301.7 2401.22   313.3 2401.32   322.2  2401.6
   333.4 2402.31   343.5 2403.47   364.5  2406.8   375.7 2408.35   398.9 2410.87
#Mann= 5 ,-1 , 0
       0    .035       0     230     .07       0   264.4    .045       0
   282.9     .07       0  362.55     .06       0
#XS Ineff= 2 , 0
          259.52 2399.95  298.01         2399.99
Permanent Ineff=
       F       F
Bank Sta=264.4,282.9
XS Rating Curve= 0 ,0
Exp/Cntr(USF)=0,0
Exp/Cntr=0.5,0.3

Type RM Length L Ch R = 1 ,3423    ,155.3,155.8,155
XS GIS Cut Line= 2
2134965.13250443199137.610703642 2135292.0223494198893.455810582
#Sta/Elev= 30
       0 2419.92    15.9 2419.63      23 2419.25    31.1 2418.32    44.9 2416.12
    55.7 2415.04    66.8 2414.84    72.3 2415.22    76.2 2415.22    84.4 2412.83
   100.8 2410.57   108.9 2408.97   117.1 2407.96   132.6 2406.98   149.5    2405
   161.3 2404.73     171 2403.86   203.5 2402.98   226.9 2401.44     240 2400.83
   267.8 2398.88   280.7  2398.5   286.1 2399.18   291.6 2399.91   302.6 2399.88
   330.1 2401.23   335.5 2401.91   358.7 2406.01   391.5 2410.42     408 2412.15
#Mann= 5 ,-1 , 0
       0    .035       0     200     .07       0   267.8    .045       0
   286.1     .07       0     320     .06       0
#XS Ineff= 2 , 0
          255.67 2399.26  291.07         2399.26
Permanent Ineff=
       F       F
Bank Sta=267.8,286.1
XS Rating Curve= 0 ,0
Exp/Cntr(USF)=0,0
Exp/Cntr=0.5,0.3

Type RM Length L Ch R = 1 ,3267    ,166.7,168.3,167.2
XS GIS Cut Line= 3
2134962.83498616199331.0943830212135376.64565511199018.556334735
2135506.99622473 198972.87076532
#Sta/Elev= 30
       0 2428.17      30  2428.5    33.9  2428.3    42.4 2426.66    50.3 2426.86
    66.2 2425.36    75.3 2421.78    79.4 2421.12   101.8 2421.46     141 2419.87
   153.3 2417.07   169.6 2414.61   179.1 2412.23   190.8  2412.3   219.2 2411.13
   251.3 2403.66   261.1 2402.61   305.5 2401.61   364.2 2397.56   371.3 2396.58
   379.5 2397.53   387.7 2398.65   420.6 2399.15   445.3 2400.38   457.9 2401.59
   490.6 2407.52   514.1 2410.78     578 2417.41   606.1 2420.92   656.7  2425.7
#Mann= 7 ,-1 , 0
       0    .035       0      80     .08       0     190    .035       0
     200     .06       0     330    .035       0   364.2    .045       0
   379.5    .035       0
Bank Sta=364.2,379.5
XS Rating Curve= 0 ,0
Exp/Cntr(USF)=0,0
Exp/Cntr=0.3,0.1

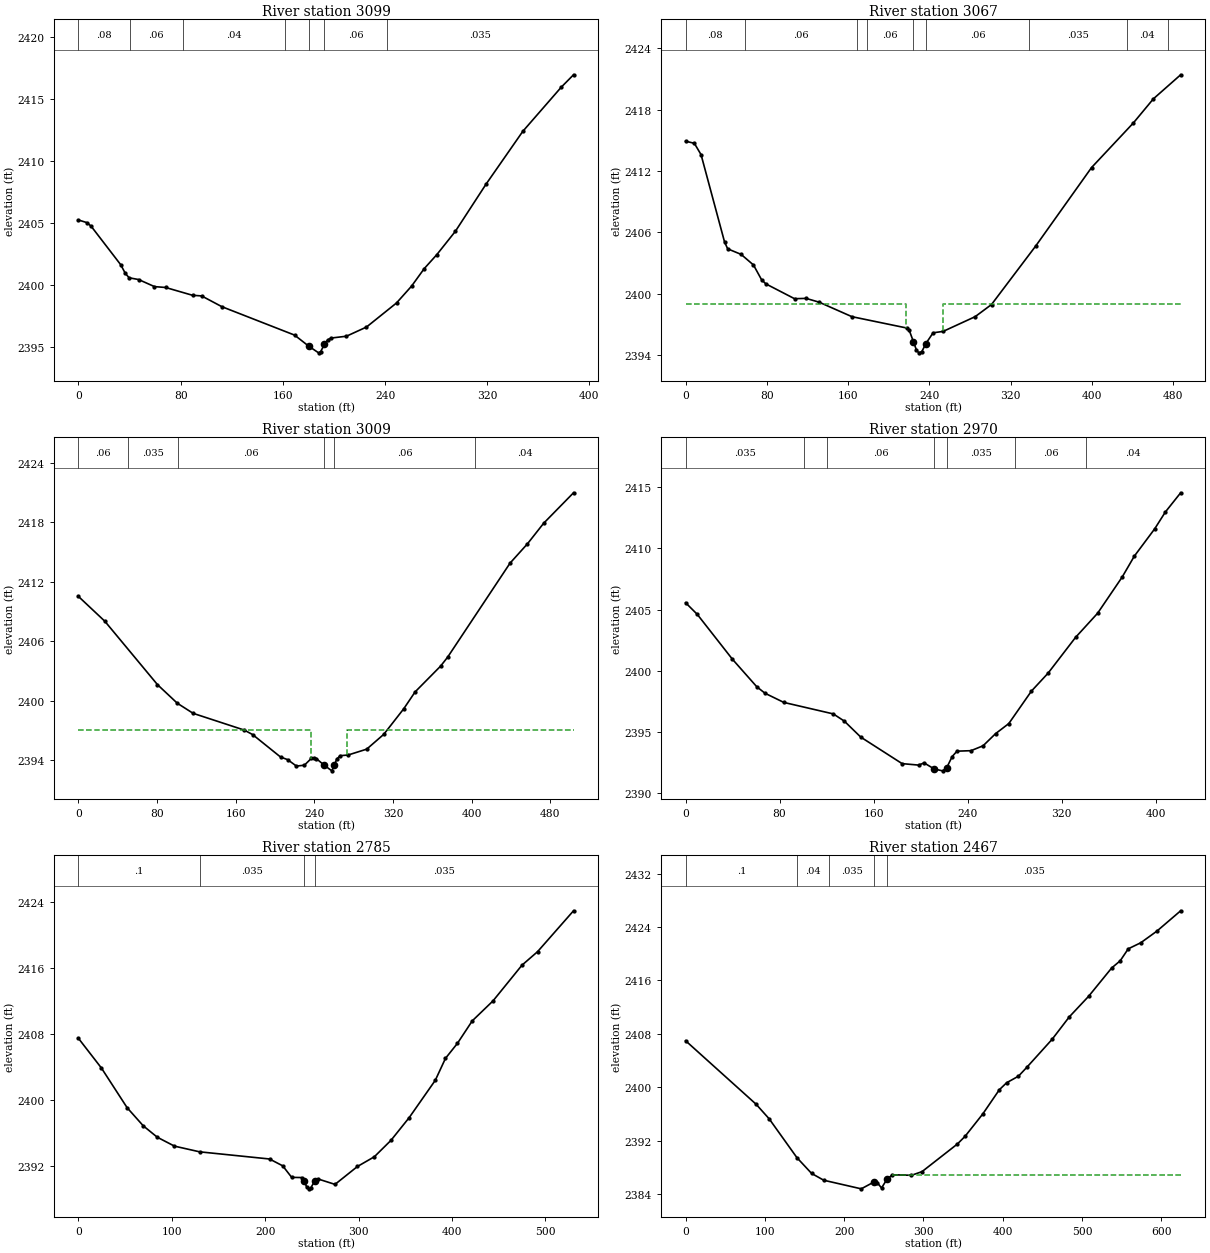
Type RM Length L Ch R = 1 ,3099    ,31.9,32,32
XS GIS Cut Line= 4
2135186.94060631199338.7004986492135228.33652378199333.526008965
2135452.39192708199170.012134963 2135489.6482528199112.575299475
#Sta/Elev= 30
       0 2405.23     6.6 2405.02     9.9 2404.73    33.1 2401.62    36.7 2400.92
    39.7 2400.57    47.1 2400.43    59.5 2399.86    68.2 2399.79    89.3 2399.16
    96.4 2399.11   112.3 2398.24   169.2 2395.95   180.22395.065     188 2394.52
   189.5 2394.59   192.62395.222     195 2395.55   197.6 2395.71   209.8 2395.86
   225.5  2396.6     249 2398.54   260.8  2399.9   270.7 2401.31   280.5 2402.43
   295.1 2404.32   319.1 2408.12   347.9 2412.38     378 2415.94   387.6 2416.94
#Mann= 7 ,-1 , 0
       0     .08       0      40     .06       0   81.72     .04       0
  161.72     .06       0   180.2    .045       0   192.6     .06       0
  241.72    .035       0
Bank Sta=180.2,192.6
XS Rating Curve= 0 ,0
Exp/Cntr(USF)=0,0
Exp/Cntr=0.5,0.3

Type RM Length L Ch R = 1 ,3067    ,57.3,57.7,57.1
XS GIS Cut Line= 4
 2135168.5783066199392.8020929172135206.43465545199387.281375376
2135503.76472871199173.5507391612135550.29649084 199104.93610687
#Sta/Elev= 30
       0 2414.92     8.6 2414.71    15.2  2413.6    38.3 2405.06    41.4 2404.38
    54.6 2403.84    66.8  2402.8    74.8 2401.35      79 2400.95   107.2  2399.5
   118.6 2399.53   131.4 2399.16   163.7 2397.74   217.7 2396.63   220.1 2396.41
   224.3 2395.28   227.1  2394.5   229.5  2394.2   232.4 2394.31   236.5 2395.09
   236.5 2395.11   243.6 2396.16   253.5  2396.3     285 2397.74   301.1 2398.93
   344.7 2404.67   399.6 2412.34   440.7  2416.7   460.5 2419.07   487.3 2421.42
#Mann= 9 ,-1 , 0
       0     .08       0   58.26     .06       0  168.26     .04       0
  178.26     .06       0   224.3    .045       0   236.5     .06       0
  338.26    .035       0  434.43     .04       0  474.43    .035       0
#XS Ineff= 2 , 0
           216.5    2399   253.5            2399
Permanent Ineff=
       F       F
Bank Sta=224.3,236.5
XS Rating Curve= 0 ,0
Exp/Cntr(USF)=0,0
Exp/Cntr=0.5,0.3

Type RM Length L Ch R = 1 ,3009    ,39.5,39.3,39.1
XS GIS Cut Line= 4
2135181.98576349199452.7413119292135256.90978725 199420.40568062
2135502.18738084 199243.742719322135589.73018756199161.720630145
#Sta/Elev= 30
       0 2410.52    26.8 2408.02    80.4 2401.61   100.6 2399.73   116.7 2398.71
   168.7 2397.02   177.3 2396.56   205.6  2394.3   212.9 2394.03   221.8 2393.38
   229.9 2393.47   236.9 2394.15   239.2 2394.22     242 2394.14   250.1 2393.47
   257.8  2392.9   260.4 2393.48   262.7 2394.06   266.3 2394.43   274.4  2394.5
   293.3 2395.09   310.7 2396.59     331 2399.17   342.6 2400.88   368.5 2403.48
   375.7 2404.39   439.2 2413.89   456.9 2415.84   473.4 2417.92   503.8    2421
#Mann= 6 ,-1 , 0
       0     .06       0      50    .035       0   101.6     .06       0
   250.1    .045       0   260.4     .06       0  403.88     .04       0
#XS Ineff= 2 , 0
           236.5    2397   273.2            2397
Permanent Ineff=
       F       F
Bank Sta=250.1,260.4
XS Rating Curve= 0 ,0
Exp/Cntr(USF)=0,0
Exp/Cntr=0.5,0.3

Type RM Length L Ch R = 1 ,2970    ,184.2,184.3,183.8
XS GIS Cut Line= 4
 2135234.5459114199462.8882510552135301.29682832199440.120496447
2135524.31733368199272.9844796672135572.44008774199219.169786958
#Sta/Elev= 30
       0 2405.56     9.9 2404.61    39.8 2400.94    60.6 2398.68    67.6 2398.15
    83.6  2397.4   125.7 2396.46   135.1 2395.87   149.1 2394.56   184.3 2392.39
   198.3 2392.27     203 2392.45   211.72391.949   218.7  2391.8   222.12392.026
   226.9 2392.97     231 2393.41   242.9 2393.45   253.2 2393.85   263.8 2394.84
   275.1 2395.67   294.4 2398.33   308.5 2399.79   331.9 2402.72   350.7  2404.7
   371.6 2407.66     382 2409.38   399.3 2411.61   408.4 2412.99   421.4 2414.56
#Mann= 7 ,-1 , 0
       0    .035       0  100.53      .1       0  120.53     .06       0
   211.7    .045       0   222.1    .035       0  280.53     .06       0
  340.53     .04       0
Bank Sta=211.7,222.1
XS Rating Curve= 0 ,0
Exp/Cntr(USF)=0,0
Exp/Cntr=0.3,0.1

Type RM Length L Ch R = 1 ,2785    ,316.4,318.4,311.9
XS GIS Cut Line= 4
2135309.75094085199638.8683604412135435.15009642 199570.25372815
2135633.64910449 199414.45790403  2135748.322263199343.603035543
#Sta/Elev= 30
       0 2407.49    24.6 2403.89    52.1 2399.08    69.4 2396.88    84.4  2395.5
   102.8 2394.42   129.7 2393.73   204.6 2392.86   218.7 2392.03   228.3 2390.63
   238.9 2390.61     242 2390.14   244.2  2389.5   246.7 2389.24   248.6 2389.32
   252.8 2390.16     257 2390.42   274.7 2389.78   298.7 2391.95   316.8 2393.13
   334.6 2395.12   354.2 2397.89   382.1 2402.41     393 2405.07   405.8 2406.89
   421.7 2409.62   443.9 2412.04   474.9 2416.37   491.6 2418.01   530.1 2422.97
#Mann= 4 ,-1 , 0
       0      .1       0     130    .035       0     242    .045       0
   252.8    .035       0
Bank Sta=242,252.8
XS Rating Curve= 0 ,0
Exp/Cntr(USF)=0,0
Exp/Cntr=0.3,0.1

Type RM Length L Ch R = 1 ,2467    ,182.4,184,183.7
XS GIS Cut Line= 4
2135533.30482415199942.7107827312135606.76426697199846.545693949
2135839.16323153199596.7835883632135901.93766448199447.193450257
#Sta/Elev= 30
       0 2406.95    88.8 2397.45   105.4 2395.25   140.4 2389.43   158.9 2387.07
   174.2 2386.05   221.5 2384.76   237.8  2385.8   241.6  2385.7   247.1 2384.89
     254  2386.2   260.9 2386.87   284.9 2386.79   298.2 2387.34   342.7 2391.47
   352.4 2392.62   374.8 2395.98   395.7 2399.61   404.9 2400.66   419.8 2401.64
   430.5 2402.99   462.2 2407.16     484 2410.54   508.2  2413.6   537.4 2417.86
   548.1 2418.93   558.3 2420.73   574.1 2421.64   594.3 2423.37   624.4 2426.43
#Mann= 5 ,-1 , 0
       0      .1       0  141.01     .04       0  181.01    .035       0
   237.8    .045       0     254    .035       0
#XS Ineff= 2 , 0
                          259.89         2386.78
Permanent Ineff=
       F       F
Bank Sta=237.8,254
XS Rating Curve= 0 ,0
Exp/Cntr(USF)=0,0
Exp/Cntr=0.3,0.1

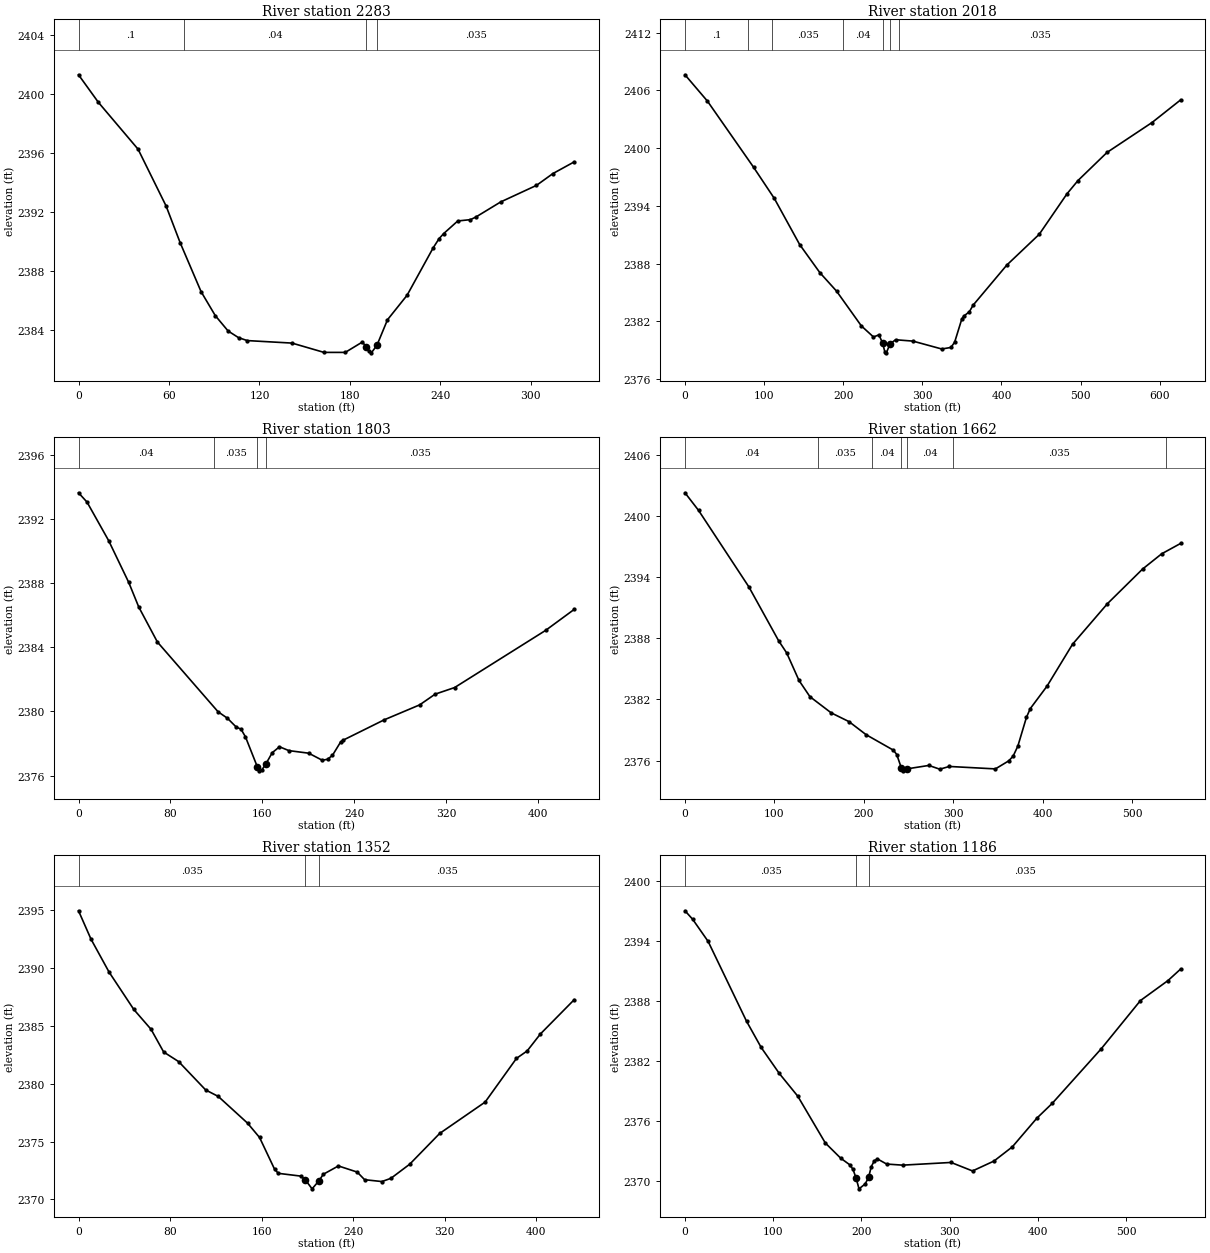
Type RM Length L Ch R = 1 ,2283    ,262.5,265,265.9
XS GIS Cut Line= 4
2135662.59126607 200045.65594132 2135716.0609928199998.510590869
2135832.19953904199856.4995962192135894.29341524199816.253565347
#Sta/Elev= 30
       0 2401.31    13.2 2399.44    39.5 2396.27    58.1 2392.42    67.4 2389.94
    81.3 2386.62    90.7    2385    99.2 2383.96   106.1 2383.51   111.9 2383.31
   141.6 2383.14   162.8 2382.51   176.9 2382.51   188.2 2383.21   190.9 2382.88
   192.5 2382.58   194.2 2382.48   197.9 2382.99   204.9 2384.72   217.9 2386.38
   235.2 2389.59   239.1 2390.21   242.2 2390.56   251.5 2391.41   259.9  2391.5
   263.4 2391.67     280  2392.7   303.7 2393.82   314.6 2394.62   328.7 2395.41
#Mann= 4 ,-1 , 0
       0      .1       0      70     .04       0   190.9    .045       0
   197.9    .035       0
Bank Sta=190.9,197.9
XS Rating Curve= 0 ,0
Exp/Cntr(USF)=0,0
Exp/Cntr=0.3,0.1

Type RM Length L Ch R = 1 ,2018    ,215.4,214.7,209.6
XS GIS Cut Line= 3
2135755.59372214 200270.399311052136048.28160682200031.808536687
2136091.91713987199786.856557593
#Sta/Elev= 30
       0 2407.63    28.4 2404.89    86.6 2398.03   112.9 2394.78   144.9 2389.99
   170.5 2387.06   191.5 2385.15   222.9 2381.53   238.2 2380.38   245.2  2380.6
   249.8 2379.72   252.6 2378.83   254.5 2378.73   259.2 2379.67   266.2 2380.09
     288 2379.95   324.5 2379.13   336.1 2379.29   340.8 2379.84   349.9 2382.26
   352.4 2382.55   359.4    2383   364.1 2383.68   406.7 2387.85   447.7 2391.05
   482.8 2395.26   496.7 2396.64   533.4 2399.56   590.3 2402.67   626.4 2405.02
#Mann= 7 ,-1 , 0
       0      .1       0      80     .04       0     110    .035       0
     200     .04       0   249.8    .045       0   259.2     .04       0
     270    .035       0
Bank Sta=249.8,259.2
XS Rating Curve= 0 ,0
Exp/Cntr(USF)=0,0
Exp/Cntr=0.3,0.1

Type RM Length L Ch R = 1 ,1803    ,138.9,140.8,141.3
XS GIS Cut Line= 4
2135964.59366648200355.7210086742136058.99793642200303.195324643
2136150.56298021200164.0732426142136280.45757721200076.767038076
#Sta/Elev= 30
       0 2393.63     7.4 2393.05    26.2 2390.65    43.7 2388.04    52.4 2386.51
    68.6 2384.33   121.4 2379.98   129.5 2379.58   137.3 2379.02   141.3  2378.9
   145.2 2378.42   155.52376.556   156.9  2376.3   159.3 2376.34   162.82376.712
   168.5 2377.43   174.8  2377.8     183 2377.56   200.2  2377.4     212 2376.96
   216.6 2377.02   220.9 2377.27     228  2378.1   230.4 2378.22   265.9 2379.48
   296.7 2380.41   310.2 2381.08   327.1 2381.49   406.2 2385.05   431.1 2386.36
#Mann= 4 ,-1 , 0
       0     .04       0  118.03    .035       0   155.5    .045       0
   162.8    .035       0
Bank Sta=155.5,162.8
XS Rating Curve= 0 ,0
Exp/Cntr(USF)=0,0
Exp/Cntr=0.3,0.1

Type RM Length L Ch R = 1 ,1662    ,299.4,310.8,315.1
XS GIS Cut Line= 4
2135980.08960459200506.4153563212136089.35718672200458.813637374
2136266.78177552200257.5881890972136420.40550485200192.676754169
#Sta/Elev= 30
       0 2402.28    15.2 2400.55    71.4 2393.05   104.7 2387.76   113.8 2386.55
   127.5 2383.86   139.7 2382.27   163.5 2380.68   183.4 2379.82   202.5 2378.54
     233 2377.02   236.8 2376.59     242 2375.25   244.3 2374.99   247.9 2375.18
   272.7 2375.52   284.9 2375.15   295.5 2375.42   347.1 2375.18     362 2375.97
   366.9 2376.43   372.2 2377.42   381.8 2380.24   386.1  2381.1   404.8  2383.3
   433.3 2387.41   472.4  2391.4   511.6 2394.79     533 2396.29   554.2 2397.31
#Mann= 7 ,-1 , 0
       0     .04       0  149.19    .035       0  209.19     .04       0
     242    .045       0   247.9     .04       0  299.19    .035       0
  537.46     .04       0
Bank Sta=242,247.9
XS Rating Curve= 0 ,0
Exp/Cntr(USF)=0,0
Exp/Cntr=0.3,0.1

Type RM Length L Ch R = 1 ,1352    ,169.1,165.5,161
XS GIS Cut Line= 4
2136088.24678559 200614.970787562136197.48601224200560.351174233
2136394.11662022200559.2012876372136478.63328505200482.158885681
#Sta/Elev= 30
       0 2394.96    10.9 2392.51    26.7 2389.66    48.3 2386.43    63.4 2384.71
    74.4 2382.75    87.5 2381.92   111.1 2379.47   122.1 2378.91   147.7  2376.6
   158.2 2375.36   171.3 2372.62   174.6 2372.26   194.3 2372.02   198.22371.692
   204.1 2370.92     2102371.604   213.9 2372.18   227.1  2372.9   243.5 2372.37
     250 2371.71   265.1 2371.55     273 2371.83   289.4 2373.05   315.6 2375.71
   355.3 2378.42   382.7  2382.2     392 2382.84   403.6 2384.31   433.1 2387.27
#Mann= 3 ,-1 , 0
       0    .035       0   198.2    .045       0     210    .035       0
Bank Sta=198.2,210
XS Rating Curve= 0 ,0
Exp/Cntr(USF)=0,0
Exp/Cntr=0.3,0.1

Type RM Length L Ch R = 1 ,1186    ,153.9,154,149.9
XS GIS Cut Line= 4
2136083.94790047200737.9328075642136174.82390937 200759.56995254
2136495.05365502200648.1386559142136577.27480592200548.607789024
#Sta/Elev= 30
       0 2397.03     8.7 2396.18    26.2 2393.97    69.8 2385.97    86.3 2383.36
   106.9 2380.75   127.8 2378.48     159  2373.8   176.4 2372.28   186.8 2371.61
   190.3 2371.17   193.8 2370.31   197.2 2369.21   204.2  2369.7     208 2370.35
   211.1 2371.44   214.6 2372.02   218.1  2372.2   228.5 2371.69   246.6 2371.58
   301.5 2371.85   325.8    2371   350.1 2371.99   370.9 2373.41   398.8 2376.29
   416.1 2377.76   471.8 2383.24   516.1 2388.05   547.3 2390.05   561.6  2391.2
#Mann= 3 ,-1 , 0
       0    .035       0   193.8    .045       0     208    .035       0
Bank Sta=193.8,208
XS Rating Curve= 0 ,0
Exp/Cntr(USF)=0,0
Exp/Cntr=0.3,0.1

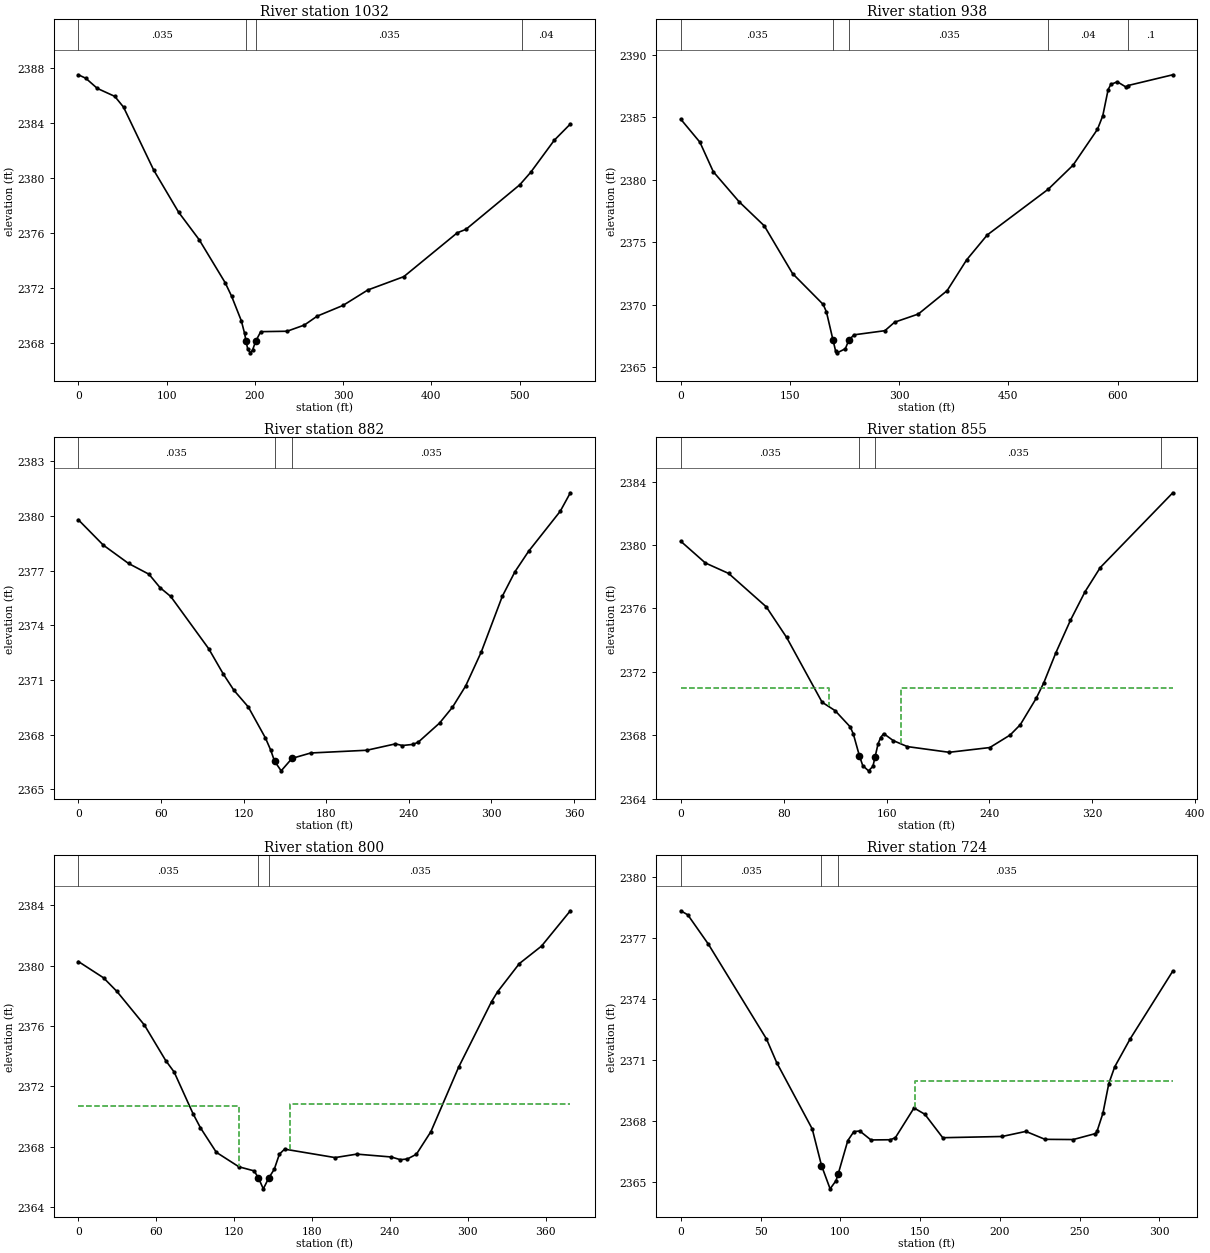
Type RM Length L Ch R = 1 ,1032    ,96.9,93.6,87
XS GIS Cut Line= 3
2136149.73989683200923.5343093182136222.11851561200917.285795467
2136654.82809978200698.587810687
#Sta/Elev= 30
       0 2387.49     8.4 2387.24    21.5  2386.5    41.3 2385.92    51.2 2385.14
    85.4 2380.56   113.6  2377.5   136.9  2375.5   166.3 2372.38   173.6  2371.4
   184.7  2369.6   188.4 2368.68   190.1  2368.1     192 2367.53     195 2367.27
   197.5 2367.48   200.9 2368.11   206.7 2368.81   236.5 2368.84   256.1 2369.29
   270.7 2369.94     300 2370.72     328 2371.84   368.8 2372.81   429.4    2376
   439.2 2376.25   500.2 2379.49   512.5 2380.39   539.3 2382.73   557.5 2383.91
#Mann= 4 ,-1 , 0
       0    .035       0   190.1    .045       0   200.9    .035       0
  502.65     .04       0
Bank Sta=190.1,200.9
XS Rating Curve= 0 ,0
Exp/Cntr(USF)=0,0
Exp/Cntr=0.3,0.1

Type RM Length L Ch R = 1 ,938     ,53.4,56.5,61.2
XS GIS Cut Line= 4
2136206.84573132201061.9879730252136322.24383785201003.086856146
2136480.91623434200831.191759948 2136758.5929282200688.146190384
#Sta/Elev= 30
       0 2384.84    26.3    2383    44.7 2380.64    80.2 2378.24   114.7 2376.32
   153.5 2372.51   195.6 2370.04   200.1 2369.44     209 2367.22   212.6 2366.34
   214.9 2366.17   226.1  2366.5   230.9  2367.2   238.1 2367.61   280.4 2367.94
   293.8 2368.62   326.3 2369.27   365.9 2371.14   392.7  2373.6     421 2375.59
   504.7 2379.24   538.8 2381.16   572.4 2384.03   579.7 2385.11   587.1 2387.21
   590.8 2387.62   599.7 2387.83   611.9  2387.4   614.3 2387.53   675.9 2388.39
#Mann= 5 ,-1 , 0
       0    .035       0     209    .045       0   230.9    .035       0
   504.7     .04       0   614.3      .1       0
Bank Sta=209,230.9
XS Rating Curve= 0 ,0
Exp/Cntr(USF)=0,0
Exp/Cntr=0.3,0.1

Type RM Length L Ch R = 1 ,882     ,27.8,27.1,26.6
XS GIS Cut Line= 2
2136280.92081982201062.9126995842136587.55724552200879.569670054
#Sta/Elev= 30
       0 2379.79    18.1  2378.4    36.5 2377.39    51.3  2376.8    59.4 2376.06
    67.1 2375.58    94.7 2372.71   105.3 2371.32     113 2370.43   123.4 2369.52
   135.9 2367.81   139.7 2367.15   142.5 2366.54   147.3 2366.01   155.22366.695
   168.8 2366.99   209.5 2367.14   230.3 2367.49   235.3  2367.4   242.9 2367.46
   246.8 2367.58   262.3 2368.63   271.7  2369.5   281.3 2370.67   292.6 2372.53
   307.9 2375.59   317.1 2376.94     327 2378.06     350 2380.26   357.3 2381.27
#Mann= 3 , 0 , 0
       0    .035       0   142.5    .045       0   155.2    .035       0
Bank Sta=142.5,155.2
XS Rating Curve= 0 ,0
Exp/Cntr(USF)=0,0
Exp/Cntr=0.5,0.3

Type RM Length L Ch R = 1 ,855     ,56.3,55.3,54.5
XS GIS Cut Line= 3
2136299.68299324201092.054792806 2136543.3673057200928.718403805
2136620.69746677200884.206408651
#Sta/Elev= 30
       0 2380.24    19.1 2378.87    37.2 2378.21    66.5  2376.1    82.3 2374.17
   109.9 2370.08     120 2369.55   131.8 2368.52   134.2 2368.07   138.9  2366.7
   141.5 2366.08     146 2365.75   149.4 2366.03  151.15 2366.65   153.4 2367.45
   155.4 2367.85   157.8  2368.1   165.2 2367.66   176.2 2367.28   208.7 2366.92
   240.3 2367.22   256.1 2368.01     264 2368.66   276.4 2370.33   282.3 2371.31
   291.6 2373.19     303 2375.25   314.4 2377.06   326.2 2378.58   382.6  2383.3
#Mann= 4 ,-1 , 0
       0    .035       0   138.9    .045       0  151.15    .035       0
  373.36     .04       0
#XS Ineff= 2 , 0
             115    2371     171            2371
Permanent Ineff=
       F       F
Bank Sta=138.9,151.15
XS Rating Curve= 0 ,0
Exp/Cntr(USF)=0,0
Exp/Cntr=0.5,0.3

Type RM Length L Ch R = 1 ,800     ,73.7,75.4,75
XS GIS Cut Line= 3
2136341.17722601201136.5667879612136578.07157311 200964.17711181
2136633.14573661200898.163559674
#Sta/Elev= 30
       0 2380.27    19.4 2379.19    29.7 2378.29    50.9 2376.06    67.3 2373.71
    73.8 2372.95    88.4 2370.18    94.1 2369.25   106.3 2367.63   123.7 2366.67
   135.4  2366.4   138.7 2365.94   142.5 2365.21   146.8 2365.95   150.9  2366.5
   154.9 2367.51   158.9 2367.84   197.8 2367.28   214.5 2367.51   241.1 2367.32
   248.1 2367.14   253.5 2367.19   260.4  2367.5   271.6    2369   292.9 2373.26
   318.3 2377.61     323 2378.27   339.7 2380.13   356.8 2381.29     379 2383.63
#Mann= 3 ,-1 , 0
       0    .035       0   138.7    .045       0   146.8    .035       0
#XS Ineff= 2 , 0
          123.39 2370.72  162.71         2370.86
Permanent Ineff=
       F       F
Bank Sta=138.7,146.8
XS Rating Curve= 0 ,0
Exp/Cntr(USF)=0,0
Exp/Cntr=0.5,0.3

Type RM Length L Ch R = 1 ,724     ,129.9,129.6,126.8
XS GIS Cut Line= 2
2136380.57765818 201167.680145032136652.71748598201022.666668712
#Sta/Elev= 30
       0 2378.33     4.4 2378.13    17.3 2376.69    53.7 2372.04    60.1 2370.88
    82.4 2367.62    88.22365.825    93.6 2364.68    97.3 2365.08    98.72365.421
   104.7 2367.05   108.5 2367.49   112.2 2367.52   119.2 2367.08   131.3 2367.09
   134.5 2367.19   146.2 2368.65     153 2368.34   164.2 2367.19   201.4 2367.25
   216.3  2367.5   228.3 2367.11     246  2367.1   259.8 2367.39   260.9  2367.5
   264.6 2368.39   268.3 2369.85     272 2370.67   281.6 2372.03   308.4 2375.37
#Mann= 3 ,-1 , 0
       0    .035       0    88.2    .045       0    98.7    .035       0
#XS Ineff= 2 , 0
                           146.7         2369.96
Permanent Ineff=
       F       F
Bank Sta=88.2,98.7
XS Rating Curve= 0 ,0
Exp/Cntr(USF)=0,0
Exp/Cntr=0.3,0.1