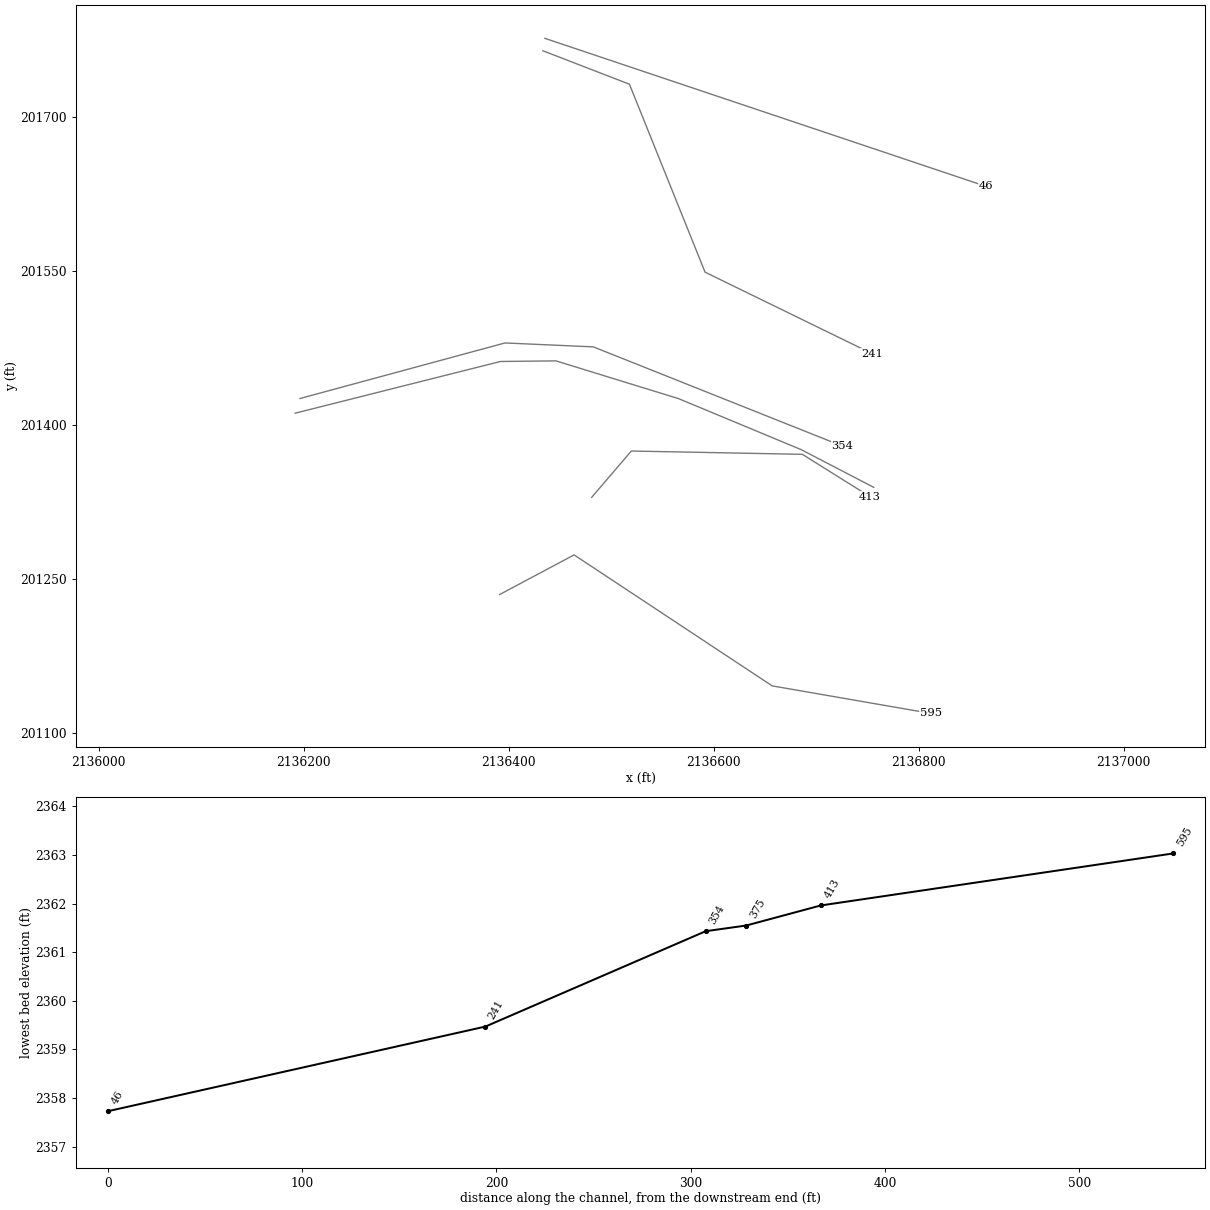
HEC-RAS study BACKCKT1.prj: BACKCKT1

--- BACKCKT1.g01 (geometry) --- (continued)

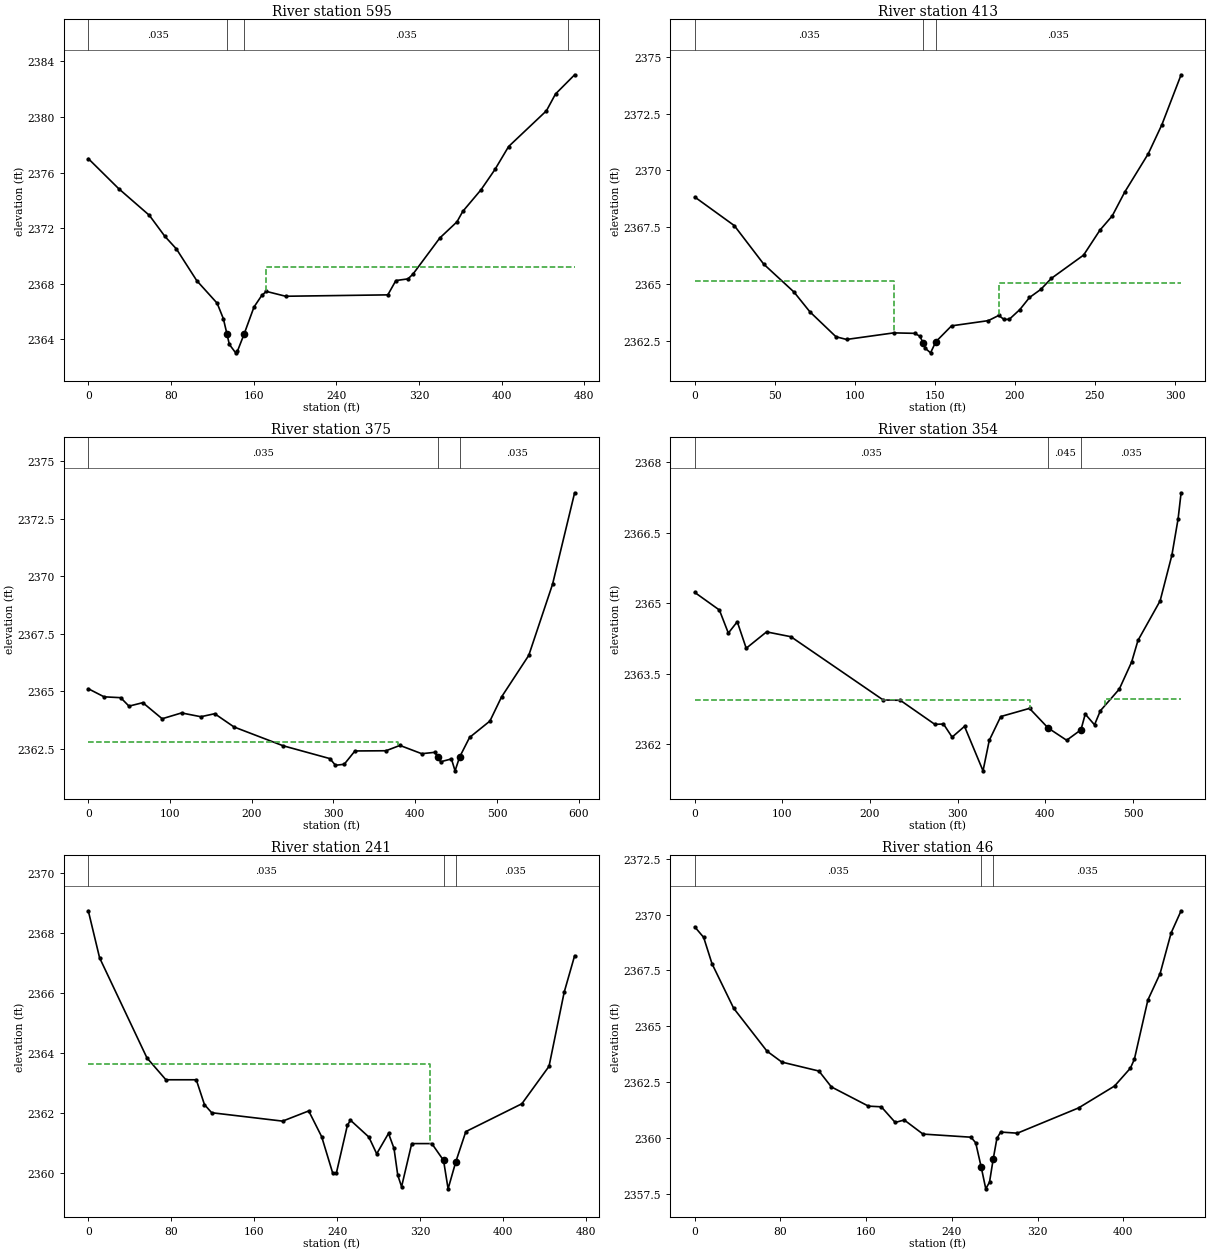
Type RM Length L Ch R = 1 ,595     ,172,181.5,181.4
XS GIS Cut Line= 4
2136391.29539831 201234.659345112136463.85340028201273.304367895
 2136657.0785142201145.5391905262136811.65860533201118.724276757
#Sta/Elev= 30
       0    2377    29.4 2374.84    59.1 2372.92      74 2371.42    85.3  2370.5
     105 2368.22   124.7  2366.6   130.7 2365.49   134.2 2364.39   136.5 2363.64
   142.6 2363.03   144.3 2363.14   150.7 2364.36   160.4 2366.33   167.9 2367.16
   172.3 2367.45     191  2367.1   289.9  2367.2   297.7 2368.23   309.4 2368.35
   314.2 2368.69   340.2 2371.29   356.8 2372.45   362.4  2373.2   380.1 2374.76
   393.6 2376.22   406.8 2377.87   443.4 2380.44   452.2 2381.65   470.7 2383.03
#Mann= 4 ,-1 , 0
       0    .035       0   134.2    .045       0   150.7    .035       0
  463.85     .04       0
#XS Ineff= 2 , 0
                           172.2         2369.18
Permanent Ineff=
       F       F
Bank Sta=134.2,150.7
XS Rating Curve= 0 ,0
Exp/Cntr(USF)=0,0
Exp/Cntr=0.3,0.1

Type RM Length L Ch R = 1 ,413     ,42.3,38.3,30.8
XS GIS Cut Line= 4
2136481.07121493201329.4713839282136519.66814767201374.608913737
2136686.47205165201371.3844081322136752.26385186201330.225824524
#Sta/Elev= 30
       0 2368.83    24.7 2367.57    43.1 2365.87      62 2364.64    71.9 2363.77
    88.2 2362.67    94.8 2362.55   124.3 2362.84   137.4 2362.82   140.7 2362.69
   142.5 2362.41     144 2362.16   147.3 2361.96   150.6 2362.45   160.4 2363.15
   183.4 2363.38   189.9 2363.61   193.2 2363.43   196.5 2363.44   203.1 2363.87
   209.1  2364.4   216.2 2364.76   222.7 2365.24   242.9 2366.27   253.1 2367.37
   260.8    2368   268.6 2369.05   283.3 2370.74   291.8 2372.02   303.8 2374.22
#Mann= 3 ,-1 , 0
       0    .035       0   142.5    .045       0   150.6    .035       0
#XS Ineff= 2 , 0
          124.42 2365.13  189.82         2365.02
Permanent Ineff=
       F       F
Bank Sta=142.5,150.6
XS Rating Curve= 0 ,0
Exp/Cntr(USF)=0,0
Exp/Cntr=0.5,0.3

Type RM Length L Ch R = 1 ,375     ,17.4,20.9,28.1
XS GIS Cut Line= 6
2136191.80952041201411.525542976 2136392.0320504201461.948218248
2136446.16168586 201462.531544212136565.73480904201425.710614215
2136685.30793222201375.9833788622136756.14715099201339.177352879
#Sta/Elev= 30
       02365.117  19.3292364.765  39.6292364.728  49.778 2364.36  66.6952364.511
  90.3782363.812 114.0612364.065 137.743  2363.9  154.662364.031 178.3432363.454
 238.2512362.639 295.575 2362.08 302.4412361.789 313.1352361.834 326.2582362.412
 364.2332362.421 381.3052362.653 407.9682362.293 423.8842362.353 427.4372362.164
 430.9912361.941 444.3052362.066 448.7572361.548 454.343 2362.15 466.523    2363
 491.3962363.712 505.6092364.759 538.9272366.567 568.0592369.662 595.0522373.634
#Mann= 3 ,-1 , 0
       0    .035       0 427.437    .045       0 454.343    .035       0
#XS Ineff= 2 , 0
          379.32 2362.81   473.9         2362.72
Permanent Ineff=
       F       F
Bank Sta=427.437,454.343
XS Rating Curve= 0 ,0
Exp/Cntr(USF)=0,0
Exp/Cntr=0.5,0.3

Type RM Length L Ch R = 1 ,354     ,112.1,113.4,107.3
XS GIS Cut Line= 4
2136196.54817975201425.8405204422136396.43966503201480.019438238
2136482.60301864201476.1970440012136725.54523716 201379.39975381
#Sta/Elev= 30
       0 2365.23  28.1072364.855  38.3052364.364  48.5032364.606    58.72364.041
  81.903 2364.39 109.6882364.287 214.962 2362.94 234.4982362.933 273.9072362.421
 283.7592362.428 293.6312362.149 307.7582362.378 328.8882361.431 336.011 2362.08
 349.0912362.587 381.9242362.761 403.1132362.344 424.3032362.082 440.6332362.305
 445.493 2362.64 456.0882362.411 462.736 2362.71 484.3412363.171 498.468 2363.75
 505.6682364.208 530.923 2365.05 544.3792366.025 551.4432366.797 554.8682367.352
#Mann= 3 ,-1 , 0
       0    .035       0 403.113    .045       0 440.633    .035       0
#XS Ineff= 2 , 0
          382.37 2362.95   467.8         2362.96
Permanent Ineff=
       F       F
Bank Sta=403.113,440.633
XS Rating Curve= 0 ,0
Exp/Cntr(USF)=0,0
Exp/Cntr=0.5,0.3

Type RM Length L Ch R = 1 ,241     ,194.3,194.3,194.3
XS GIS Cut Line= 4
2136433.34207422201765.0257204262136517.83997553201732.377056499
2136591.58805599201549.0626315282136754.41320956201469.643062337
#Sta/Elev= 30
       0 2368.75    10.9 2367.18    56.6 2363.84    74.9 2363.11   104.2 2363.11
   112.1 2362.28   119.1 2362.01   187.5 2361.73   212.7 2362.07   225.2 2361.21
   235.8    2360   239.4    2360     250 2361.59     253 2361.76   270.7  2361.2
   278.3 2360.64   289.7 2361.32     295 2360.82   298.6 2359.93   302.3 2359.54
   312.1 2360.98   331.5 2360.98   342.8 2360.42   347.2 2359.47   354.6 2360.37
   364.3 2361.38   418.4 2362.31   444.6 2363.56   459.2 2366.03   469.3 2367.25
#Mann= 3 ,-1 , 0
       0    .035       0   342.8    .045       0   354.6    .035       0
#XS Ineff= 2 , 0
           329.3 2363.62
Permanent Ineff=
       F       F
Bank Sta=342.8,354.6
XS Rating Curve= 0 ,0
Exp/Cntr=0.3,0.1

Type RM Length L Ch R = 1 ,46      ,28.9,29.6,30.1
XS GIS Cut Line= 2
2136435.33365159201777.1309322352136865.63984141 201632.72702303
#Sta/Elev= 30
       0 2369.45     8.3 2368.98    16.1  2367.8    36.3 2365.81    67.4 2363.89
    81.3  2363.4   115.9    2363   127.5 2362.29   162.1 2361.43   174.1  2361.4
   187.1  2360.7   195.5 2360.81     213 2360.18   257.8 2360.04   262.2 2359.79
   267.4 2358.69   271.6 2357.73   275.1 2358.03   278.5 2359.05     282 2359.99
   285.5 2360.27   301.1 2360.22   358.2 2361.35   391.8 2362.33   406.6 2363.13
   410.3 2363.53   422.9 2366.18   434.3 2367.36   444.6 2369.18   453.9 2370.17
#Mann= 3 ,-1 , 0
       0    .035       0   267.4    .045       0   278.5    .035       0
Bank Sta=267.4,278.5
XS Rating Curve= 0 ,0
Exp/Cntr=0.3,0.1
LCMann Table=0

Chan Stop Cuts=-1
Use User Specified Reach Order=0
Composite Channel Slope=5